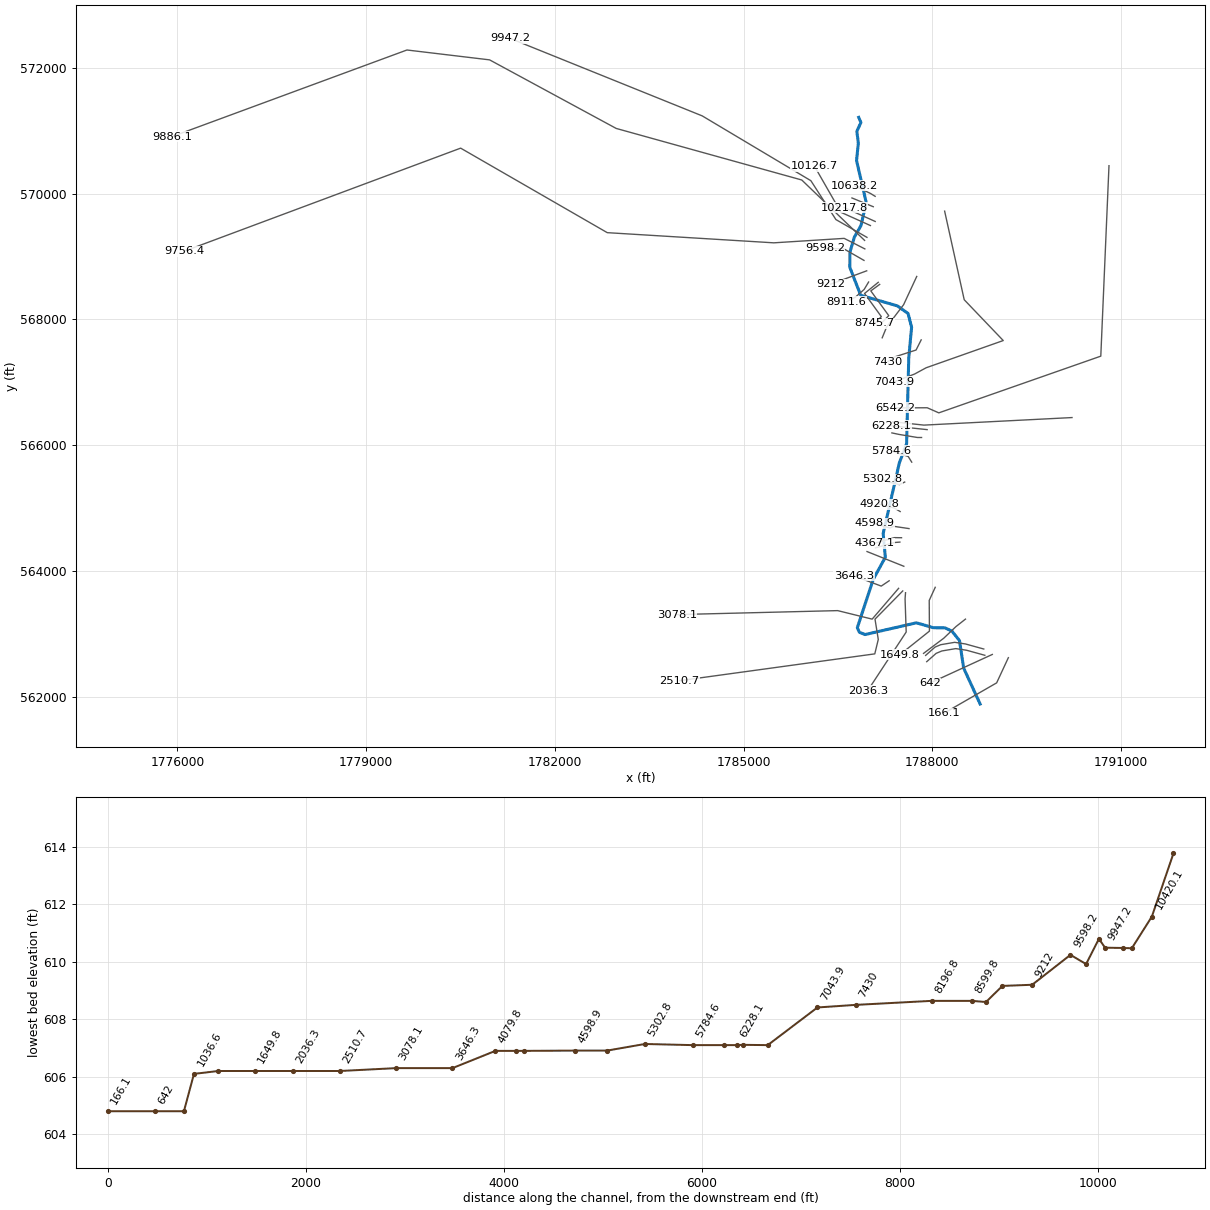
--- POCATALCK.prj (project) ---

Proj Title=POCATALCK
Current Plan=p01
Default Exp/Contr=0,0
English Units
Geom File=g01
Flow File=f01
Plan File=p01
BEGIN DESCRIPTION:
END DESCRIPTION:
DSS Export Rating Curves= 0
DSS Export Rating Curve Sorted= 0
DSS Export Volume Flow Curves= 0
DXF OffsetX= 0
DXF OffsetY= 0
DXF ScaleX= 0
DXF ScaleY= 0

--- POCATALCK.p01 (plan) ---

Plan Title=Floodplain
Program Version=4.00
Geom File=g01
Flow File=f01
K Sum by GR=0
Std Step Tol=0.01
Critical Tol=0.01
Num of Std Step Trials=20
Max Error Tol=0.3
Flow Tol Ratio=0.001
Split Flow NTrial=30
Split Flow Tol=0.02
Split Flow Ratio=0.02
Log Output Level=0
Friction Slope Method=1
Unsteady Friction Slope Method=2
Unsteady Bridges Friction Slope Method=1
Global Log Level=0
CheckData=False
Run HTab=0
Run UNet=0
Run PostProcess=0
UNET Theta=0
UNET Theta Warmup=0
UNET ZTol=0
UNET ZSATol=0
UNET MxIter=0
UNET MaxInSteps=0
UNET DtIC=0
UNET DtMin=0
UNET MaxCRTS=0
UNET WFStab=0
UNET SFStab=0
UNET WFX=0
UNET SFX=0
UNET DSS MLevel=0
UNET DZMax Abort=0
UNET Convert EG Bridges=0
UNET Use Existing IB Tables=0
UNET Froude Limit=0
UNET Froude Power=0
Write IC File=0
Echo Input=False
Echo Output=False
Write Detailed=0

--- POCATALCK.f01 (steady flow) ---

Flow Title=NFF Regression Equation
Program Version=4.00
Number of Profiles=1
Profile Names=P100yr
River Rch & RM=POCATALCK,Main      ,10638.2
4673.009
River Rch & RM=POCATALCK,Main      ,9598.2
5835.531
River Rch & RM=POCATALCK,Main      ,6542.2
9020.013
River Rch & RM=POCATALCK,Main      ,2510.7
9247.455
Boundary for River Rch & Prof#=POCATALCK,Main      ,1
Up Type=0
Dn Type=3
Dn Slope=0.004137

--- POCATALCK.g01 (geometry) ---

Geom Title=USGS 10m DEM
Program Version=4.10

River Reach=POCATALCK       ,Main
Reach XY= 30
     1786829.619      571210.646     1786864.505      571129.739
     1786800.269       570990.85     1786823.503      570800.718
     1786795.291      570526.195     1786949.082      569858.172
     1786866.379      569492.683     1786760.079      569306.911
      1786689.88      569069.005     1786688.578      568827.252
     1786861.282       568383.42     1787444.615      568215.017
     1787614.754      568093.489      1787670.31      567874.739
     1787625.171      567390.364     1787590.864      566023.856
     1787474.856      565717.153     1787218.779      564597.362
     1787252.775      564219.053     1787062.671      563871.701
     1786807.462      563100.868      1786840.09      563027.266
      1786930.17      562990.896     1787745.661      563177.751
     1788019.098      563099.626      1788201.39      563097.456
     1788312.067      563045.372     1788431.425      562895.633
     1788498.076      562457.605     1788759.814      561886.927

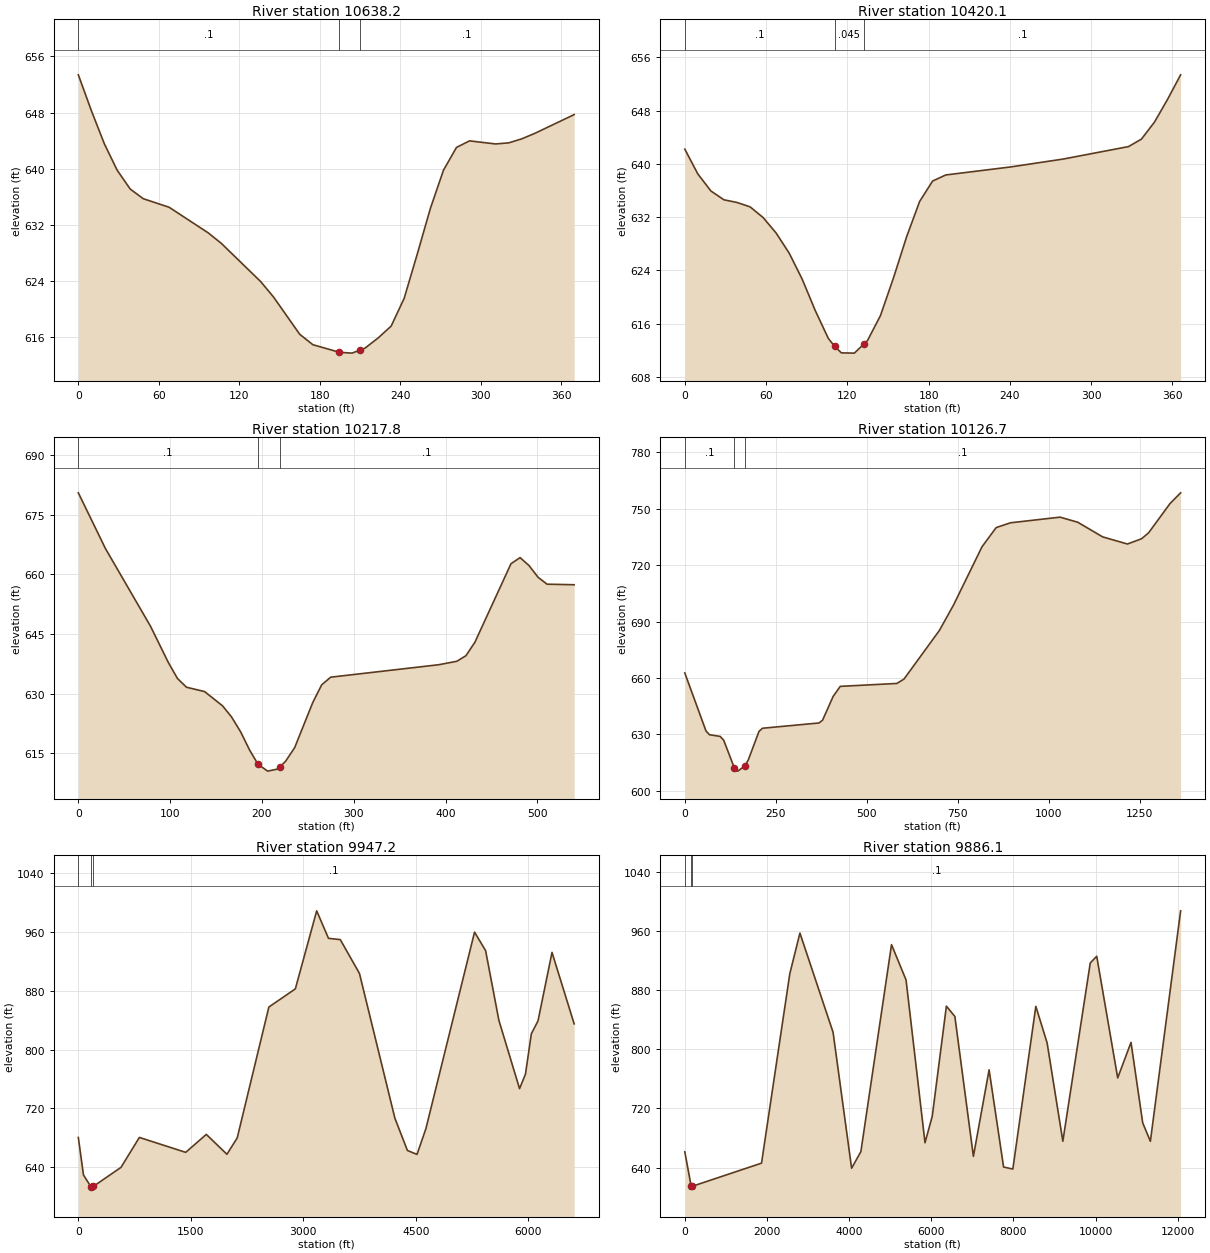
Type RM Length L Ch R = 1 ,10638.2 ,213,218.1,222.8
XS GIS Cut Line= 3
      1787091.12      569956.673     1787016.901      570002.246
     1786761.693       570123.34
#Sta/Elev= 30
       0  653.38     9.7  648.29    19.4  643.56      29  639.79    38.7  637.12
    48.4  635.75    67.7  634.53    96.8  630.89   106.6  629.39   135.8  623.98
   145.5  621.76     165  616.46   174.8  614.97   194.6  613.89     204  613.77
   209.6  614.18   213.7  614.48   223.5  615.93   233.2  617.62   242.9  621.58
   252.7   627.9   262.4  634.35   272.2  639.81   281.9  643.05   291.6  643.98
   311.1  643.54   320.9   643.7   330.6  644.27   340.4  645.06   369.6  647.72
#Mann= 3 , 0 , 0
       0      .1       0   194.6    .045       0   209.6      .1       0
Bank Sta=194.6,209.6
XS Rating Curve= 0 ,0
Exp/Cntr=0.3,0.1

Type RM Length L Ch R = 1 ,10420.1 ,203.1,202.3,201.5
XS GIS Cut Line= 2
     1787061.172      569791.309     1786722.631      569930.632
#Sta/Elev= 30
       0  642.21     9.6  638.49    19.3  635.92    28.9   634.6    38.5   634.2
    48.2  633.54    57.8  631.94    67.4  629.62    77.1  626.58    86.7  622.67
    96.3  617.98     106  613.77  110.54  612.61   115.6  611.61   125.2  611.57
   132.4  612.97   134.9  613.46   144.5  617.22   154.1  622.88   163.8  629.06
   173.4  634.35     183  637.42   192.7  638.33   240.8  639.54   279.4  640.72
   327.6  642.59   337.2  643.72   346.8  646.27   356.5   649.7   366.1  653.37
#Mann= 3 , 0 , 0
       0      .1       0  110.54    .045       0   132.4      .1       0
Bank Sta=110.54,132.4
XS Rating Curve= 0 ,0
Exp/Cntr=0.3,0.1

Type RM Length L Ch R = 1 ,10217.8 ,91.1,91.1,91.2
XS GIS Cut Line= 2
     1787091.554      569557.368     1786598.933      569778.722
#Sta/Elev= 30
       0   680.5    29.5  666.49    78.6  646.94    98.2  637.74     108  633.78
   117.8  631.58   137.5  630.49   157.1   626.9   166.9   624.1   176.8  620.36
   186.6  615.76   195.7  612.21   206.2  610.47     216  610.94  220.02  611.63
   225.8  612.96   235.7   616.4   255.3   627.7   265.1  632.19   274.9  634.11
   392.8  637.25   412.4  638.12   422.2  639.51     432  642.91   471.3  662.66
   481.2   664.2     491  662.18   500.8  659.25   510.6  657.51   540.1  657.37
#Mann= 3 , 0 , 0
       0      .1       0   195.7    .045       0  220.02      .1       0
Bank Sta=195.7,220.02
XS Rating Curve= 0 ,0
Exp/Cntr=0.3,0.1

Type RM Length L Ch R = 1 ,10126.7 ,181.7,179.5,177.3
XS GIS Cut Line= 3
     1787015.599      569492.263     1786546.498      569703.049
     1786125.024      570438.315
#Sta/Elev= 30
       0  662.67    58.2  631.84    67.9  629.82      97  628.94   106.7  626.98
   135.8  612.35   145.6  610.48     165  613.24   174.7  616.59   203.8  631.62
   213.5  633.28   368.7  636.08   378.4  637.55   407.5  650.22     427  655.54
   582.5  657.09     602   659.4   699.4   685.3   738.3  698.85   816.3  729.74
   855.2  739.93   894.2  742.48  1030.6  745.49  1079.3  742.78  1147.5  735.01
  1215.7  731.21  1254.6  734.01  1274.1  737.22  1332.6   752.7  1361.8  758.42
#Mann= 3 , 0 , 0
       0      .1       0   135.8    .045       0     165      .1       0
Bank Sta=135.8,165
XS Rating Curve= 0 ,0
Exp/Cntr=0.3,0.1

Type RM Length L Ch R = 1 ,9947.2  ,61,61.1,61
XS GIS Cut Line= 5
     1786960.912      569304.329      1786467.39      569587.038
     1786069.305      570205.154     1784342.182      571235.248
     1781286.627      572467.887
#Sta/Elev= 30
       0   680.6    68.6  629.71   166.7  613.89   176.5  610.49  199.72  614.14
   568.8  640.06   813.8   680.7  1431.5  660.45  1706.2  684.82  1980.8  657.84
  2118.2  680.04    2540  857.79  2893.1  882.49  3177.6  988.48  3334.6  951.14
    3492  949.39  3747.7  903.46  4219.8  706.92    4387  662.97  4514.9  657.65
  4632.9  692.42    5282  959.55  5429.5   934.4  5606.6  839.63    5882  746.97
  5960.6  766.61  6039.3  821.55  6127.8  838.92  6314.7     932  6609.8  834.98
#Mann= 3 , 0 , 0
       0      .1       0   166.7    .045       0  199.72      .1       0
Bank Sta=166.7,199.72
XS Rating Curve= 0 ,0
Exp/Cntr=0.3,0.1

Type RM Length L Ch R = 1 ,9886.1  ,128.4,129.7,130.6
XS GIS Cut Line= 6
     1786923.151      569256.152     1785924.454      570216.288
     1782974.713      571035.903     1780962.569       572125.68
     1779649.098      572282.578      1775918.05      570907.008
#Sta/Elev= 30
       0  661.28   156.2  614.58     166   610.8  186.13  614.74  1867.8  645.95
  2556.6  902.36  2802.6  957.31  3609.4   823.1  4060.8  639.11  4286.4  661.51
  5032.7  941.64  5386.2  893.89  5847.8  673.59  6024.6  709.51  6368.3  858.41
  6574.6  844.47  7025.8  655.16  7407.9  772.28  7760.6  640.73    7986  637.97
  8545.5  858.14  8820.4  808.68  9203.3   675.6    9871  916.92 10028.1  925.94
 10538.6   761.3 10862.7  809.38 11147.4  700.48   11334  675.51 12070.4  987.42
#Mann= 3 , 0 , 0
       0      .1       0   156.2    .045       0  186.13      .1       0
Bank Sta=156.2,186.13
XS Rating Curve= 0 ,0
Exp/Cntr=0.3,0.1

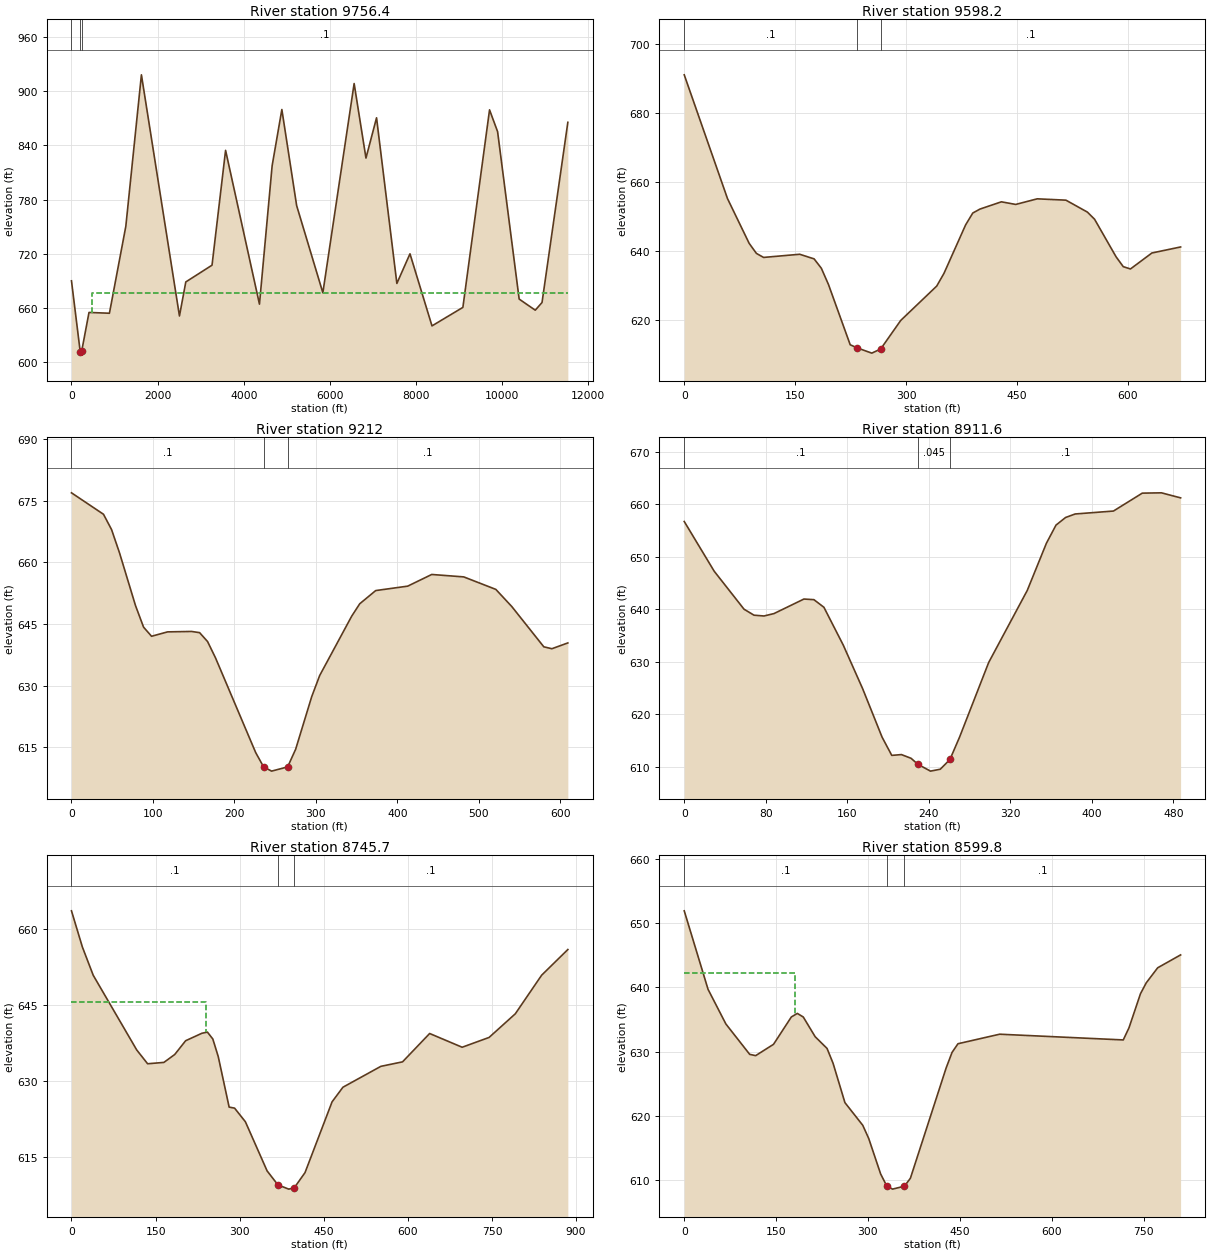
Type RM Length L Ch R = 1 ,9756.4  ,160,158.2,156.9
XS GIS Cut Line= 6
     1786927.058       569121.17     1786598.933       569288.27
     1785480.116        569217.5     1782833.009      569379.151
       1780502.5      570722.577     1776109.023      569084.091
#Sta/Elev= 30
       0  690.05  202.62  611.59   219.5  609.92  235.69  611.74     407     655
   881.5  654.12  1262.3  750.46  1624.4  918.31    2508   651.1  2655.3  688.79
  3264.5  707.37  3579.5  834.61  4366.3  664.21  4660.8  817.58  4886.6  879.86
  5230.2  773.36  5838.9   676.8  6565.4  908.64  6840.3  826.07    7086  870.69
  7557.9  687.14  7862.6  719.98  8373.8   640.1  9091.4  660.61  9710.7   879.5
  9897.5  855.36 10398.8   669.8 10772.4  657.51 10929.7  666.01 11529.3  865.67
#Mann= 3 , 0 , 0
       0      .1       0  202.62    .045       0  235.69      .1       0
#XS Ineff= 2 , 0
                           478.3          676.79
Permanent Ineff=
       F       F
Bank Sta=202.62,235.69
XS Rating Curve= 0 ,0
Exp/Cntr=0.3,0.1

Type RM Length L Ch R = 1 ,9598.2  ,365.8,386.2,406.2
XS GIS Cut Line= 3
     1786913.487      568938.335     1786591.988      569122.906
     1786291.641      569128.114
#Sta/Elev= 30
       0  691.06    58.5  655.11    87.8  642.11    97.6   639.2   107.3  638.03
   156.1  638.95   175.6  637.61   185.4  634.88   195.1  630.12   224.4  612.67
   234.1  611.74   253.6  610.24   265.6  611.44   292.7  619.73   341.4  629.72
   351.2  633.41   380.4  647.46   390.1  650.92   399.8  652.07   428.8  654.18
   448.2  653.42   477.3  655.05   516.1  654.66   545.1  651.19   554.8  649.12
   583.9   638.2   593.6  635.35   603.3  634.68   632.3  639.32   671.1  641.07
#Mann= 3 , 0 , 0
       0      .1       0   234.1    .045       0   265.6      .1       0
Bank Sta=234.1,265.6
XS Rating Curve= 0 ,0
Exp/Cntr=0.3,0.1

Type RM Length L Ch R = 1 ,9212    ,291.8,300.4,308.5
XS GIS Cut Line= 2
     1786956.679      568772.622     1786385.391      568560.406
#Sta/Elev= 30
       0  676.93    39.3  671.71    49.2  667.99      59   662.3    78.6  649.49
    88.5  644.24    98.3  642.02     118  643.09   147.4  643.19   157.3   642.9
   167.1  640.73   176.9  636.73   226.1  613.74   235.9  610.22   245.7   609.2
   265.4  610.23   275.2  614.51   294.9   627.3   304.7  632.46     344   646.9
   353.9  649.93   373.5  653.14   412.8  654.22   442.3  657.06   481.6  656.47
     521  653.43   540.6  649.25   579.9  639.45   589.8  638.99   609.4   640.4
#Mann= 3 , 0 , 0
       0      .1       0   235.9    .045       0   265.4      .1       0
Bank Sta=235.9,265.4
XS Rating Curve= 0 ,0
Exp/Cntr=0.3,0.1

Type RM Length L Ch R = 1 ,8911.6  ,123.5,166,202.4
XS GIS Cut Line= 4
     1786987.061       568594.67     1786916.641      568477.072
     1786781.224      568357.281     1786631.919       568277.42
#Sta/Elev= 30
       0  656.71    29.4  647.24    58.7     640    68.5  638.86    78.3  638.71
    88.1  639.17   117.5  641.94   127.3  641.82   137.1  640.37   156.1  633.16
   175.1  624.87   194.2  615.63   203.7  612.16   213.2  612.31   222.7   611.6
   229.2  610.48   241.7  609.16   251.3  609.52   260.8  611.38   270.3  615.66
   298.8  629.84   336.7  643.58   355.5  652.57   364.9  656.02   374.3  657.47
   383.7  658.14   421.3   658.7   449.6  662.11   468.4  662.17   487.2  661.21
#Mann= 3 , 0 , 0
       0      .1       0   229.2    .045       0   260.8      .1       0
Bank Sta=229.2,260.8
XS Rating Curve= 0 ,0
Exp/Cntr=0.3,0.1

Type RM Length L Ch R = 1 ,8745.7  ,149.5,145.9,148.1
XS GIS Cut Line= 4
     1787140.599       568589.92     1786922.445      568412.485
      1787189.21      568044.781     1787085.044      567937.142
#Sta/Elev= 30
       0  663.68    19.4  656.53    38.8  650.92   116.4  636.14   135.8  633.41
   164.8  633.68   184.2  635.25   203.6  637.97   232.7  639.45   242.4  639.68
   252.1  638.31   261.8  634.82   281.2  624.83   290.9  624.63   310.2  621.93
   348.9  612.21   368.2  609.44   387.5   608.6   397.2  608.84   416.5  611.86
   464.8  625.88   484.2  628.77   551.8   632.9   590.5  633.79   638.8   639.4
   696.8  636.68   744.8  638.62   791.6   643.3   838.5  650.93   885.3  656.02
#Mann= 3 , 0 , 0
       0      .1       0   368.2    .045       0   397.2      .1       0
#XS Ineff= 2 , 0
          240.04  645.71
Permanent Ineff=
       F       F
Bank Sta=368.2,397.2
XS Rating Curve= 0 ,0
Exp/Cntr=0.3,0.1

Type RM Length L Ch R = 1 ,8599.8  ,437.2,403,368.9
XS GIS Cut Line= 4
     1787163.169      568556.934      1787021.99      568453.624
     1787307.266      568060.406     1787203.099      567952.767
#Sta/Elev= 30
       0  651.88    38.9  639.68      68   634.3   106.9  629.58   116.6  629.38
   145.8  631.14   174.9  635.39   184.7  635.94   194.4  635.38   213.8  632.32
   233.2   630.5     243   628.2   262.4  622.08   291.5  618.56   301.2  616.52
   320.7     611   330.4  609.18   340.1  608.64   359.6   609.1   369.3  610.33
   427.6  627.45   437.3  629.88     447  631.23     515  632.71   716.9  631.82
   726.3  633.72     745     639   754.4  640.69   773.1  643.03   810.5  645.03
#Mann= 3 , 0 , 0
       0      .1       0   330.4    .045       0   359.6      .1       0
#XS Ineff= 2 , 0
          180.69  642.24
Permanent Ineff=
       F       F
Bank Sta=330.4,359.6
XS Rating Curve= 0 ,0
Exp/Cntr=0.3,0.1

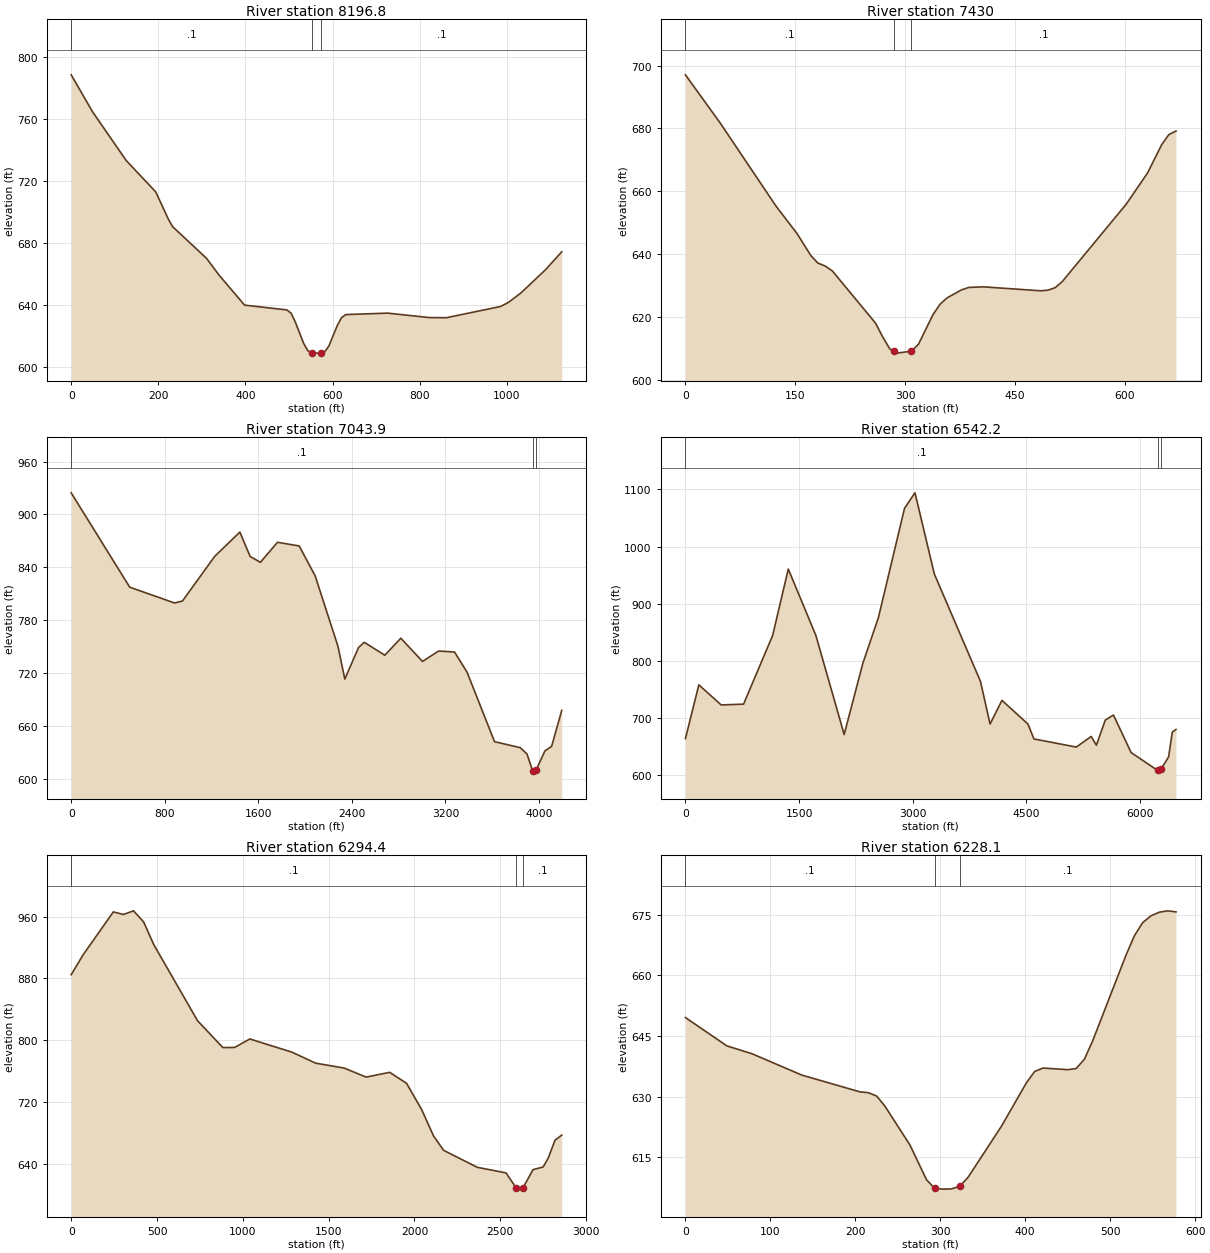
Type RM Length L Ch R = 1 ,8196.8  ,780.2,766.8,753.4
XS GIS Cut Line= 4
     1787752.029      568683.127     1787543.377      568234.017
      1787274.28      567881.586     1787203.099      567707.975
#Sta/Elev= 30
       0  788.33    48.6  764.66   126.2  733.05   194.2  712.71   223.3     695
     233  690.26   310.7  669.86   339.8  658.91   398.1  639.63   495.2  636.54
   504.8  634.44   514.5  628.78   533.8   614.9   543.4  610.17     553  608.67
   562.7  608.64   573.9  608.78     582  609.51   591.6  613.21   610.9  626.43
   620.5  631.47   630.2  633.52   726.6  634.46     823  631.57   861.5  631.51
   985.5  638.73  1004.3  641.45  1032.4  647.46  1088.7   662.4  1126.3  674.07
#Mann= 3 , 0 , 0
       0      .1       0     553    .045       0   573.9      .1       0
Bank Sta=553,573.9
XS Rating Curve= 0 ,0
Exp/Cntr=0.3,0.1

Type RM Length L Ch R = 1 ,7430    ,384.6,386.1,386.9
XS GIS Cut Line= 4
     1787822.891      567674.989     1787741.294      567513.531
     1787395.808       567402.42     1787293.377      567329.503
#Sta/Elev= 30
       0  697.04    47.6  681.67   123.8  655.22   152.3  646.56   171.4  639.48
   180.9  637.14   190.7  636.22   200.5  634.66   259.4  618.08   269.2   613.7
     279  609.83   284.9  609.03   288.8   608.5   308.4  609.12   318.2  611.36
   337.8  620.69   347.6  624.09   357.5  626.13   377.1  628.66   386.9   629.4
   406.5  629.59     485  628.33   494.8  628.52   504.6  629.31   514.4  631.27
   601.8  655.93   630.9  665.86   650.2  674.86   659.9  678.04   669.6  679.15
#Mann= 3 , 0 , 0
       0      .1       0   284.9    .045       0   308.4      .1       0
Bank Sta=284.9,308.4
XS Rating Curve= 0 ,0
Exp/Cntr=0.3,0.1

Type RM Length L Ch R = 1 ,7043.9  ,510.5,501.7,493.2
XS GIS Cut Line= 6
     1788195.374      569721.437     1788506.663      568312.895
     1789127.057      567664.239     1787901.406       567231.61
     1787716.988      567131.586     1787394.072      567008.322
#Sta/Elev= 30
       0   924.6   500.5  817.42   883.2  799.48   951.9   801.7  1226.6  852.33
  1442.5  879.98  1530.3  852.31  1618.1  845.65  1764.5  868.43  1949.9  864.22
  2086.4  830.26  2281.6  750.18  2340.1  712.94  2457.4  748.82  2506.2  754.74
  2682.2  740.12    2819   759.4  3004.6  733.04  3141.5  744.83  3278.3  743.76
  3385.8  720.79  3620.3  641.88  3840.1  635.07  3897.7  627.96  3945.7  608.83
  3955.3  608.41  3974.5  609.15  4051.3  631.42  4108.9  636.64  4195.3  677.44
#Mann= 3 , 0 , 0
       0      .1       0  3945.7    .045       0  3974.5      .1       0
Bank Sta=3945.7,3974.5
XS Rating Curve= 0 ,0
Exp/Cntr=0.3,0.1

Type RM Length L Ch R = 1 ,6542.2  ,250.3,247.8,245.2
XS GIS Cut Line= 5
     1790807.807      570443.629     1790677.599      567416.285
     1788102.954      566514.858     1787918.551      566595.996
     1787402.926      566593.392
#Sta/Elev= 30
       0  663.98   177.1  758.09   472.2   722.9   767.4  724.32  1151.1  844.35
  1357.7  960.66  1721.7  844.61  2095.5  671.18  2341.5  795.58  2548.1  876.07
  2892.4 1067.09  3030.1 1094.06  3285.3  952.06  3893.6  764.44  4021.2  689.58
  4178.2  730.95  4521.6  689.37  4600.2  663.44  5159.5   649.2  5355.7  667.75
  5424.4  652.48  5542.2  696.45  5650.1  705.26  5882.8  639.62  6231.9  608.43
  6251.4   607.1  6279.8     611  6377.8  631.97  6426.5  675.47  6475.1  679.98
#Mann= 3 , 0 , 0
       0      .1       0  6231.9    .045       0  6279.8      .1       0
Bank Sta=6231.9,6279.8
XS Rating Curve= 0 ,0
Exp/Cntr=0.3,0.1

Type RM Length L Ch R = 1 ,6294.4  ,66.3,66.3,66.3
XS GIS Cut Line= 3
     1790220.113      566440.187     1787866.599      566320.177
     1787367.769       566373.34
#Sta/Elev= 30
       0  884.73    68.7  910.22   245.5  966.05   304.4   962.7   363.3  967.43
   422.2  953.02   481.1   923.7   736.4  825.08   883.7  790.42   952.4  790.54
  1040.8  801.52  1286.3  784.45  1423.8  770.24  1590.7  763.83  1718.3  752.17
  1855.8  758.33    1954  744.11  2042.4  709.95  2111.1  675.98    2170  657.35
  2366.4  635.33  2533.6  628.13  2592.6  608.62  2612.3  607.11    2632  608.74
    2691  632.36    2750  635.84  2779.5  647.38  2818.9  670.42  2858.2  677.02
#Mann= 3 , 0 , 0
       0      .1       0  2592.6    .045       0    2632      .1       0
Bank Sta=2592.6,2632
XS Rating Curve= 0 ,0
Exp/Cntr=0.3,0.1

Type RM Length L Ch R = 1 ,6228.1  ,132.9,131.5,130.2
XS GIS Cut Line= 2
     1787917.249       566248.34      1787343.03      566309.538
#Sta/Elev= 30
       0  649.58    48.9  642.56    78.3  640.63     137  635.34   205.5  631.18
   215.3  630.99   225.1  630.15   234.9  627.64   264.3  618.04   283.8  609.43
   293.6  607.26   303.4   607.1   313.2  607.16     323   607.8   332.8  610.05
   371.9  622.63   401.3  633.38   411.1  636.23   420.9  637.08   450.2  636.68
     460  636.96   469.8   639.3   479.6  643.91   518.7  665.05   528.5  669.82
   538.3  673.09   548.1  674.78   557.9  675.67   567.7  676.01   577.5  675.75
#Mann= 3 , 0 , 0
       0      .1       0   293.6    .045       0     323      .1       0
Bank Sta=293.6,323
XS Rating Curve= 0 ,0
Exp/Cntr=0.3,0.1

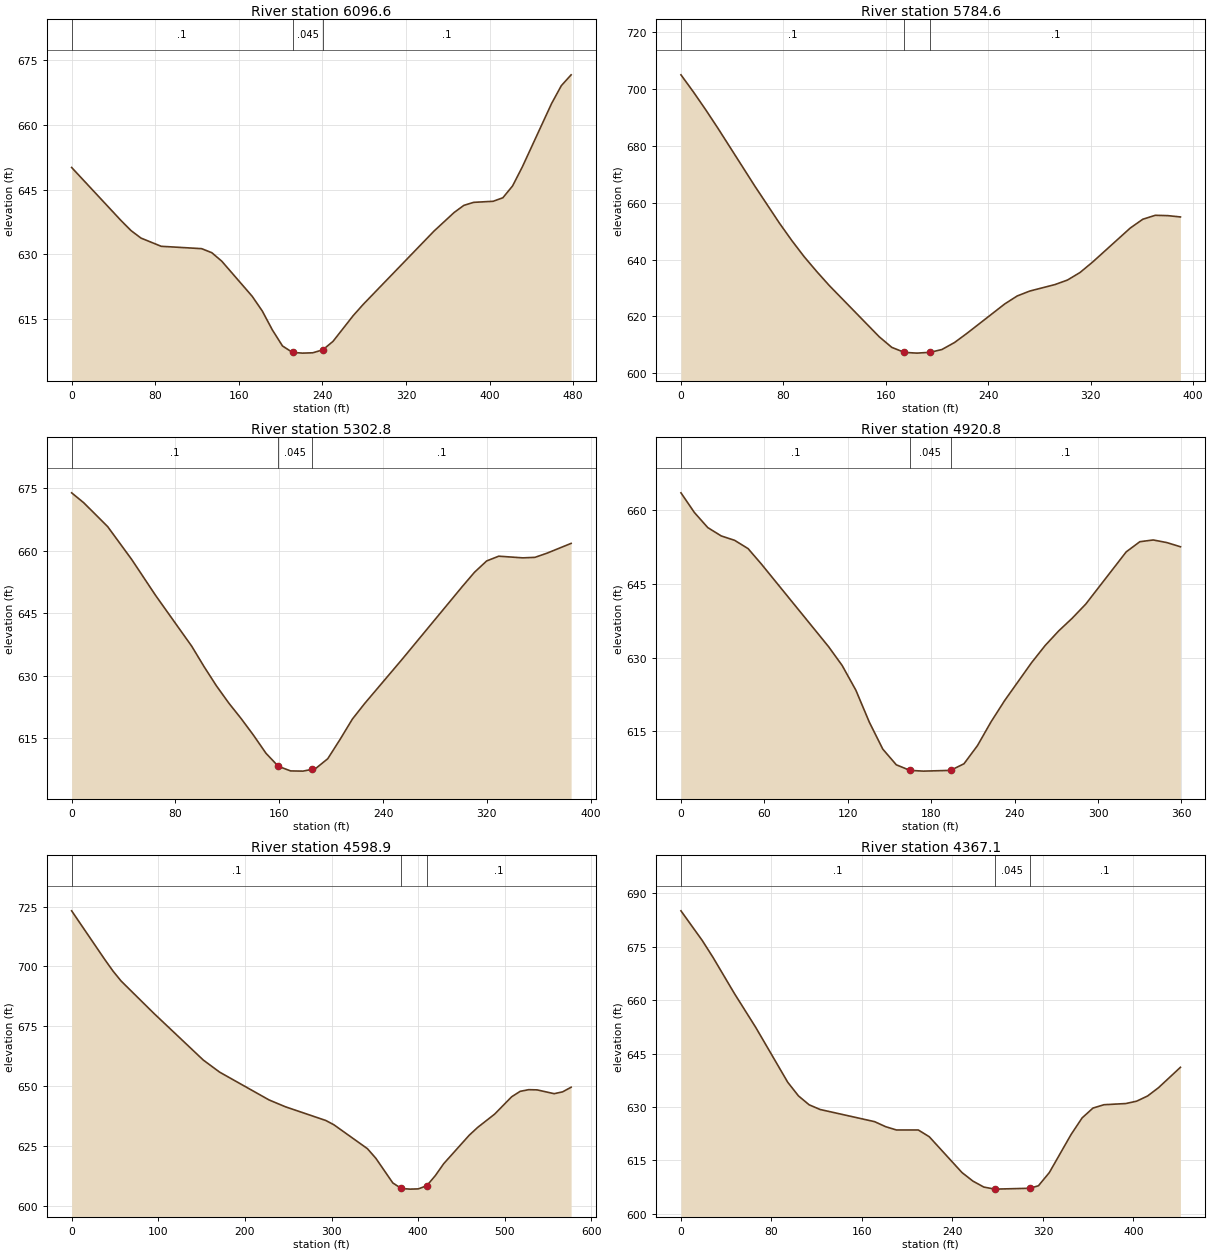
Type RM Length L Ch R = 1 ,6096.6  ,315.5,312,308.4
XS GIS Cut Line= 4
     1787828.707       566123.34     1787762.301       566123.34
     1787466.728      566172.819     1787357.353      566196.257
#Sta/Elev= 30
       0  650.16    47.4  637.82    56.9  635.51    66.4  633.78    85.7  631.88
   124.4  631.33   134.1   630.4   143.7  628.42   172.8  620.28   182.4  616.89
   192.1  612.48   201.8  608.76   211.4  607.26   221.1   607.1   230.8  607.18
   240.4  607.87   250.1  609.82   269.4  615.78   279.1  618.42   346.8  635.41
   366.1  639.73   375.4  641.38   384.7  642.07   403.4  642.32   412.7  643.14
     422  645.89   431.3  650.29   459.3  664.99   468.6  669.13     478  671.65
#Mann= 3 , 0 , 0
       0      .1       0   211.4    .045       0   240.4      .1       0
Bank Sta=211.4,240.4
XS Rating Curve= 0 ,0
Exp/Cntr=0.3,0.1

Type RM Length L Ch R = 1 ,5784.6  ,479.7,481.8,483.4
XS GIS Cut Line= 3
     1787672.457      565731.413     1787616.467      565821.257
     1787346.936        565911.1
#Sta/Elev= 30
       0  704.99     9.6  699.05    19.2  692.79    28.9  686.18    57.7  665.84
      77  652.75    86.6  646.68    96.2  641.02   105.9  635.87   115.7  630.93
   154.8  612.86   164.6  609.13   174.4  607.37   184.2   607.1   194.7  607.39
   203.8  608.38   213.6  610.83   223.4  614.09   252.8   624.4   262.6  627.22
   272.4  628.94     292  631.21   301.8  632.81   311.6  635.46   321.4  639.12
   350.8  651.09   360.6  654.19   370.4  655.58   380.2  655.46     390     655
#Mann= 3 , 0 , 0
       0      .1       0   174.4    .045       0   194.7      .1       0
Bank Sta=174.4,194.7
XS Rating Curve= 0 ,0
Exp/Cntr=0.3,0.1

Type RM Length L Ch R = 1 ,5302.8  ,382.4,382,381.7
XS GIS Cut Line= 4
     1787560.478      565415.007     1787477.144      565374.642
     1787310.478      565415.007     1787198.499      565460.579
#Sta/Elev= 30
       0  673.86     9.3  671.49    27.8  665.75    46.3  657.88    64.8  649.23
    92.6  637.07   102.1  632.18   111.6  627.59   121.2  623.43   130.7  619.72
   140.2  615.74   149.8  611.42   159.3   608.3   168.8  607.19   178.3  607.14
   185.5  607.58   187.9  607.72   197.4  610.11   206.9  614.74   216.4  619.62
     226   623.4   254.6   633.9   301.3  651.46   310.6  654.84   319.9  657.53
   329.2  658.67   347.8  658.27   357.1  658.39   366.4  659.39     385  661.74
#Mann= 3 , 0 , 0
       0      .1       0   159.3    .045       0   185.5      .1       0
Bank Sta=159.3,185.5
XS Rating Curve= 0 ,0
Exp/Cntr=0.3,0.1

Type RM Length L Ch R = 1 ,4920.8  ,322.6,321.9,321.3
XS GIS Cut Line= 3
     1787488.863      564946.257     1787397.717      565000.944
     1787152.926      565064.746
#Sta/Elev= 30
       0  663.57     9.7  659.55    19.3  656.49      29  654.79    38.6   653.9
    48.3  652.21      58  649.02   106.3  632.21     116   628.4   125.8   623.4
   135.5  616.88   145.2  611.39   154.9   608.2   164.7  607.06   174.4  606.91
   193.9  607.06   203.6  608.41   213.3  612.11     223  616.92   232.8  621.26
   252.2  628.99     262  632.49   271.7  635.45   281.4  638.03   291.2  640.92
   320.3  651.55   330.1  653.62   339.8  653.97   349.5  653.44   359.3  652.59
#Mann= 3 , 0 , 0
       0      .1       0   164.7    .045       0   193.9      .1       0
Bank Sta=164.7,193.9
XS Rating Curve= 0 ,0
Exp/Cntr=0.3,0.1

Type RM Length L Ch R = 1 ,4598.9  ,521.7,519.1,516.5
XS GIS Cut Line= 4
     1787629.422      564675.399     1787385.277      564711.726
     1787326.103      564684.538     1787072.197      564758.757
#Sta/Elev= 30
       0  723.26      38  703.04    47.5   698.2      57  693.95    94.9   680.4
   151.9  660.89   170.9   655.8   227.8  644.21   246.8  641.33   293.4   635.6
   302.6  633.84   341.4  623.82   351.1  619.82   370.7   609.5   380.5   607.2
   390.3  606.91   400.1  607.01   409.9  608.33   419.7  612.53   429.5  617.57
   458.9  629.45   468.7  632.73   488.3  638.29   507.9  645.53   517.7  647.79
   527.5  648.49   537.3   648.4   556.9  646.81   566.7  647.58   576.5  649.51
#Mann= 3 , 0 , 0
       0      .1       0   380.5    .045       0   409.9      .1       0
Bank Sta=380.5,409.9
XS Rating Curve= 0 ,0
Exp/Cntr=0.3,0.1

Type RM Length L Ch R = 1 ,4367.1  ,74.3,74.3,74.3
XS GIS Cut Line= 3
     1787510.395      564530.177     1787397.089      564531.783
     1787081.576      564441.636
#Sta/Elev= 30
       0  685.11    18.9  676.74    28.3  672.04    47.2   661.9    66.1  652.35
    94.4  636.93   103.9  633.09   113.3   630.6     123  629.28   171.2  625.86
   180.9  624.45   190.5  623.52   209.8  623.52   219.5  621.62   248.4  611.56
   258.1  609.15   267.7  607.48   277.4   606.9   308.4  607.14     316  607.85
   325.6  611.55   344.9  622.29   354.6  626.92   364.2  629.68   373.9  630.62
   393.2  630.95   402.8  631.62   412.5  633.08   422.2  635.43   441.5  641.14
#Mann= 3 , 0 , 0
       0      .1       0   277.4    .045       0   308.4      .1       0
Bank Sta=277.4,308.4
XS Rating Curve= 0 ,0
Exp/Cntr=0.3,0.1

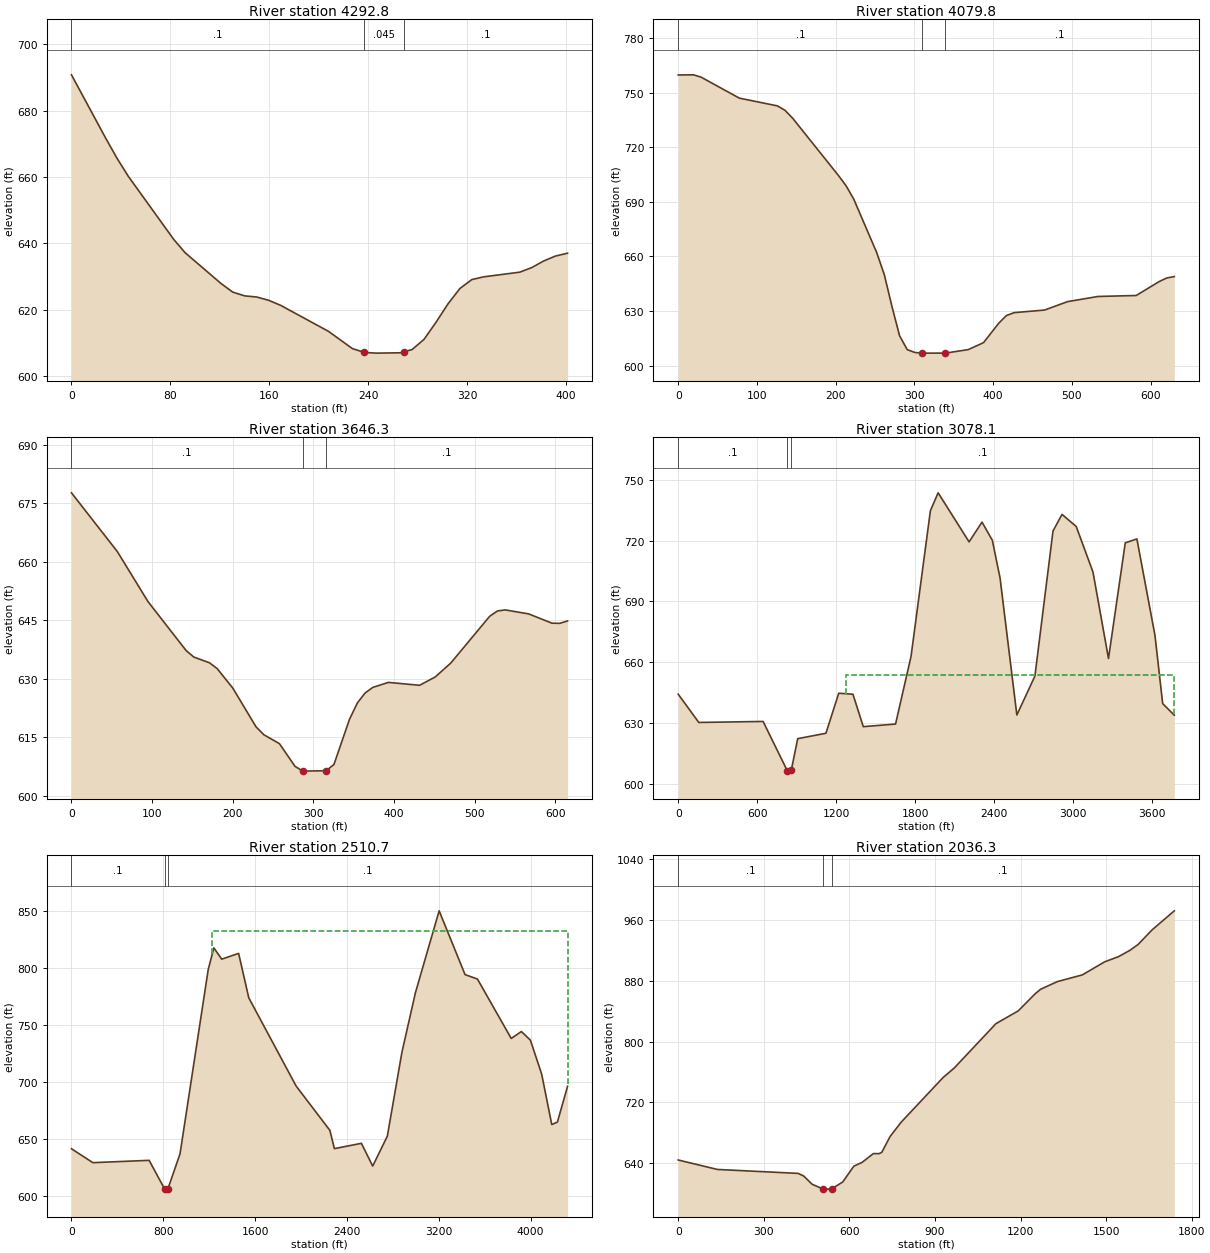
Type RM Length L Ch R = 1 ,4292.8  ,228.3,213.1,197.9
XS GIS Cut Line= 3
     1787484.353      564460.733     1787392.864       564453.69
     1787095.465      564368.719
#Sta/Elev= 30
       0  690.82    27.5  671.83    36.7  665.74    45.9  660.25    82.6  641.24
    91.8  637.21   120.8  627.93   130.4   625.3   140.1  624.16   149.8  623.82
   159.4  622.84   169.1  621.31   207.8  613.47   227.1  608.28   236.7  607.11
   246.4   606.9   265.7     607   268.5  607.28   275.4  607.97   285.1  611.07
   294.7  616.17   304.4  621.73   314.1   626.4   323.7  629.08   333.4  629.91
   362.4  631.31   372.1  632.68   381.7  634.67   391.4  636.18   401.1  637.03
#Mann= 3 , 0 , 0
       0      .1       0   236.7    .045       0   268.5      .1       0
Bank Sta=236.7,268.5
XS Rating Curve= 0 ,0
Exp/Cntr=0.3,0.1

Type RM Length L Ch R = 1 ,4079.8  ,432.7,433.5,433.7
XS GIS Cut Line= 2
     1787546.957      564076.441     1786961.954      564310.406
#Sta/Elev= 30
       0  759.68    19.4  759.76    29.1  758.47    77.6  746.96     126   742.7
   135.7  740.24   145.4  735.88   203.6   704.4   213.2   698.8   222.9   691.5
     252  662.19   261.7  650.02   271.4   632.6   281.1  616.45   290.8  608.83
   300.5  607.25   310.2   606.9   339.3  606.91   368.3  608.83   387.7  612.65
   407.1  623.36   416.8  627.54   426.5  629.13   465.3  630.56   494.4  635.18
   533.1  638.02   581.6  638.55   610.7  646.19   620.4  648.18     630  648.95
#Mann= 3 , 0 , 0
       0      .1       0   310.2    .045       0   339.3      .1       0
Bank Sta=310.2,339.3
XS Rating Curve= 0 ,0
Exp/Cntr=0.3,0.1

Type RM Length L Ch R = 1 ,3646.3  ,565.5,568.2,570.8
XS GIS Cut Line= 3
     1787313.516      563845.996     1787187.648      563761.361
      1786753.62      563924.121
#Sta/Elev= 30
       0  677.63    56.9  662.57    94.8  649.78   142.2   637.2   151.7  635.54
     171  634.08   180.6   632.6     200   627.6   228.9  617.65   238.6  615.62
   257.9  613.34   277.2  607.53   286.9   606.3   315.8   606.4   325.5     608
   344.8  619.59   354.5  623.75   364.1  626.33   373.8  627.77   393.1  629.04
   431.7   628.3     451  630.42   470.4     634   518.6  645.98   528.3  647.35
     538  647.62   566.9   646.6   595.9  644.22   605.6  644.18   615.2  644.79
#Mann= 3 , 0 , 0
       0      .1       0   286.9    .045       0   315.8      .1       0
Bank Sta=286.9,315.8
XS Rating Curve= 0 ,0
Exp/Cntr=0.3,0.1

Type RM Length L Ch R = 1 ,3078.1  ,522.5,567.4,612.2
XS GIS Cut Line= 4
      1787463.69       563725.77     1787043.551      563236.187
      1786494.94      563371.604     1783935.845      563308.212
#Sta/Elev= 30
       0  644.25   156.4  630.31   645.1  630.81   830.2   606.3   859.5  606.81
   908.2  622.32  1122.5  624.97    1220  644.74  1327.9  644.22  1406.4  628.24
  1651.6  629.52  1769.3  662.87  1916.4  734.75  1975.2  743.59  2210.6  719.39
  2308.7  729.15  2387.2  720.17    2446  701.51  2573.5     634  2710.8   653.2
  2848.2  724.73  2916.8  732.95  3024.7  726.98  3152.2  704.47  3269.9  661.86
  3397.4   718.9  3485.7  720.86    3623  673.31  3681.8   639.6  3770.1  633.89
#Mann= 3 , 0 , 0
       0      .1       0   830.2    .045       0   859.5      .1       0
#XS Ineff= 2 , 0
                         1275.46          653.67
Permanent Ineff=
       F       F
Bank Sta=830.2,859.5
XS Rating Curve= 0 ,0
Exp/Cntr=0.3,0.1

Type RM Length L Ch R = 1 ,2510.7  ,477.5,474.4,471.4
XS GIS Cut Line= 5
     1787529.662      563684.104      1787088.69      563236.187
     1787140.773       562913.27     1787085.217      562684.104
     1783983.588      562257.865
#Sta/Elev= 30
       0  641.63   186.6  629.42   676.7  631.47   811.3  606.36     821   606.2
   840.2  606.38     946  637.24  1191.4  798.88  1240.5  817.92  1309.2  808.04
  1456.4   813.1  1544.8   774.1    1957  696.74  2251.4  657.78  2290.7  641.74
  2526.2  646.41  2624.4  626.42  2751.9  652.65  2879.5   726.5  2997.3  778.77
  3203.4  850.46  3429.1  794.49  3537.1  790.59  3831.5  738.43  3919.8  744.52
  3998.4  736.97  4096.5  707.23  4184.8  662.86  4233.9  665.09  4322.2  696.41
#Mann= 3 , 0 , 0
       0      .1       0   811.3    .045       0   840.2      .1       0
#XS Ineff= 2 , 0
                         1226.75          832.65
Permanent Ineff=
       F       F
Bank Sta=811.3,840.2
XS Rating Curve= 0 ,0
Exp/Cntr=0.3,0.1

Type RM Length L Ch R = 1 ,2036.3  ,386.5,386.5,386.5
XS GIS Cut Line= 4
     1787573.933      563656.217     1787566.575      563558.107
     1787584.349      563031.217     1786973.151      562100.344
#Sta/Elev= 30
       0  644.46   137.4  632.05   420.6  626.86   440.1  623.37   469.4  612.62
   508.4  606.26   518.2   606.2   537.7  606.35   576.8  615.66   615.8  636.39
   645.1  641.46   684.2   652.9   703.7  652.78   713.5  654.45   742.8  675.34
   781.9  694.27   928.4  752.75   967.5  765.23    1114  823.62  1192.1  840.35
  1250.8  862.64  1270.3  868.73  1328.9  878.78  1416.8  887.63    1495  904.78
  1543.8  911.62  1582.9  919.75  1612.2  927.57    1661  946.64  1739.2  971.79
#Mann= 3 , 0 , 0
       0      .1       0   508.4    .045       0   537.7      .1       0
Bank Sta=508.4,537.7
XS Rating Curve= 0 ,0
Exp/Cntr=0.3,0.1

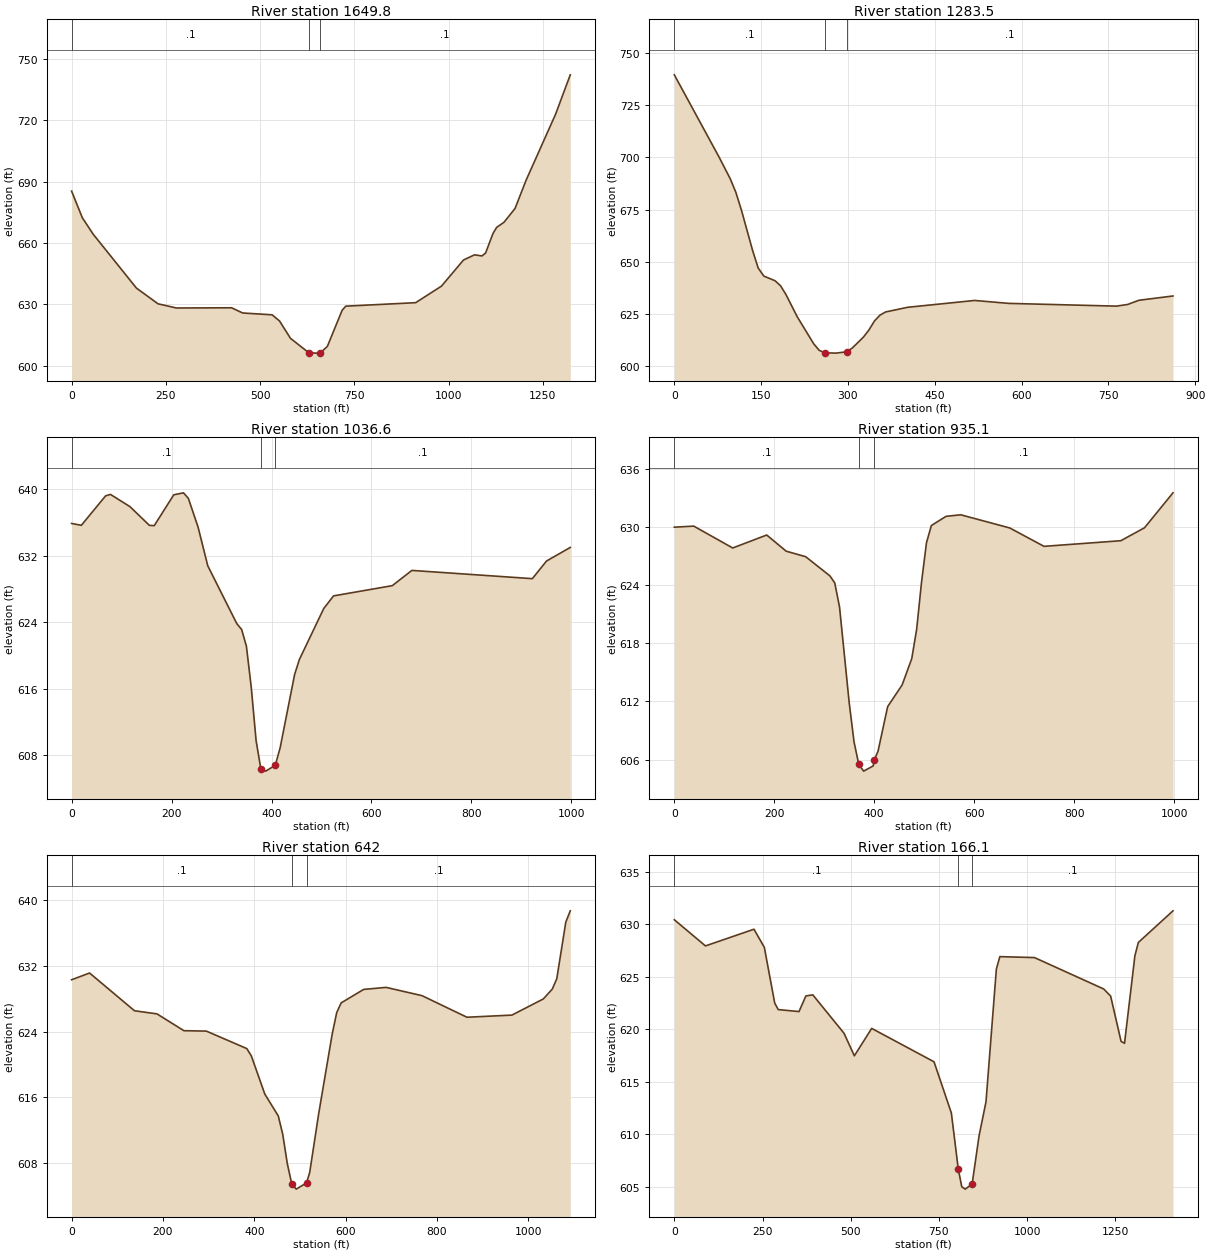
Type RM Length L Ch R = 1 ,1649.8  ,385.2,366.2,347.3
XS GIS Cut Line= 4
     1788046.088       563742.24     1787950.602      563533.906
     1787953.707       563045.54     1787480.617      562667.936
#Sta/Elev= 30
       0  685.41    28.6  672.36    57.3  664.35   171.9  638.02   229.2  630.32
     278  628.27   424.5  628.37   453.8  625.83     532  624.93   551.5  621.95
   580.8   613.4   629.6  606.35   649.2   606.2   658.9   606.2   678.5  609.48
   717.6  627.12   727.3  629.16   912.8  630.87   981.2  638.96  1039.7  651.74
    1069  654.27  1088.6  653.72  1098.3  655.17  1117.8  664.68  1127.6  667.69
  1147.1  670.19  1176.4  676.94  1205.7  690.74  1283.8  722.96  1322.9  742.28
#Mann= 3 , 0 , 0
       0      .1       0   629.6    .045       0   658.9      .1       0
Bank Sta=629.6,658.9
XS Rating Curve= 0 ,0
Exp/Cntr=0.3,0.1

Type RM Length L Ch R = 1 ,1283.5  ,267.8,246.9,226
XS GIS Cut Line= 4
     1788526.624      563236.513     1788374.714      563117.155
     1788181.572      562932.693     1787860.391      562691.808
#Sta/Elev= 30
       0  739.57    77.3  700.16    96.6  689.78   106.3  683.29   115.9  674.79
   135.2  655.47   144.9     647   154.6  643.14   173.9  640.91   183.5  638.52
   193.2  634.13   212.3  623.67   240.9  610.65   250.4  607.54     260  606.36
     279   606.2   297.9  606.83   307.6  608.67   326.7  613.86   336.3   617.3
   345.8  621.58   355.4  624.41   364.9  625.91     403  628.16     519  631.44
   577.8  630.04   763.8  628.72   783.4  629.52     803  631.54   861.7  633.59
#Mann= 3 , 0 , 0
       0      .1       0     260    .045       0   297.9      .1       0
Bank Sta=260,297.9
XS Rating Curve= 0 ,0
Exp/Cntr=0.3,0.1

Type RM Length L Ch R = 1 ,1036.6  ,101.6,101.5,101.4
XS GIS Cut Line= 6
     1788817.422      562761.252     1788526.624      562841.547
     1788355.183      562867.589      1788132.96      562829.829
     1788042.683      562791.634     1787893.377       562659.69
#Sta/Elev= 30
       0  635.85    19.5  635.63    68.1  639.17    77.8  639.34   116.8  637.87
   155.7  635.62   165.4  635.59   204.4  639.29   223.8  639.53   233.6  638.87
     253  635.43   272.5  630.76   330.6  623.81   340.2  623.12   349.8   621.1
   359.5  616.16   369.1   609.8   378.8  606.32   388.4   606.1   407.6   606.8
   417.3  608.91   446.2   617.7   455.8  619.51   504.5  625.63   524.1  627.15
   641.7  628.38   680.9  630.21   921.9  629.22   950.3  631.34   997.8  632.97
#Mann= 3 , 0 , 0
       0      .1       0   378.8    .045       0   407.6      .1       0
Bank Sta=378.8,407.6
XS Rating Curve= 0 ,0
Exp/Cntr=0.3,0.1

Type RM Length L Ch R = 1 ,935.1   ,279.4,293.1,306.7
XS GIS Cut Line= 6
     1788834.783      562661.426     1788543.985      562741.721
     1788372.544      562767.763     1788150.322      562730.002
     1788060.044      562691.808     1787910.738      562559.863
#Sta/Elev= 30
       0  630.01    38.9  630.12   116.8  627.86   184.9   629.2   223.8  627.53
   262.8  626.96   311.3  624.98     321  624.25   330.6  621.75   349.8  611.93
   359.5  607.85   369.1  605.49   378.8   604.8     398  605.34  400.35  605.98
   407.6  606.86   426.9  611.47   455.8   613.7   475.1  616.43   484.9  619.47
   494.7  624.35   504.5  628.39   514.3  630.18   543.7  631.13   573.1  631.29
   671.1  629.93   739.7  628.03   893.4  628.61   940.8  629.95   997.8  633.56
#Mann= 3 , 0 , 0
       0      .1       0   369.1    .045       0  400.35      .1       0
Bank Sta=369.1,400.35
XS Rating Curve= 0 ,0
Exp/Cntr=0.3,0.1

Type RM Length L Ch R = 1 ,642     ,474,475.9,477.8
XS GIS Cut Line= 2
     1788953.273      562674.881     1787961.085      562219.151
#Sta/Elev= 30
       0  630.32    39.4  631.14   137.7  626.54   186.9  626.16   245.9  624.11
   295.1  624.06   383.6  621.93   393.5  621.04     423  616.39   452.5  613.72
   462.3  611.48   472.2  607.94     482  605.43   491.8   604.8  514.44  605.56
   521.3  606.83     541     614   570.5  623.68   580.4  626.31   590.2   627.5
   639.4  629.14   688.6  629.39   767.2  628.38   865.6  625.75     964  626.01
  1032.8  627.98  1052.5  629.19  1062.3  630.45    1082  637.34  1091.8  638.72
#Mann= 3 , 0 , 0
       0      .1       0     482    .045       0  514.44      .1       0
Bank Sta=482,514.44
XS Rating Curve= 0 ,0
Exp/Cntr=0.3,0.1

Type RM Length L Ch R = 1 ,166.1   ,160.4,166.1,171.5
XS GIS Cut Line= 3
     1789208.481      562623.665     1789022.141      562223.213
     1788179.835      561738.249
#Sta/Elev= 30
       0  630.44    88.3  627.95   225.8  629.54   255.2  627.81   284.6  622.51
   294.5  621.89   353.4   621.7     373  623.19   392.6  623.29     481  619.64
   510.4  617.49   559.5   620.1   736.2  616.92   785.3  612.05   804.9  606.72
   814.8  605.03   824.6   604.8   844.2  605.28   863.8  609.86   883.5  613.11
   912.9  625.74   922.8  626.93  1020.9  626.84  1217.3  623.85  1236.9  623.17
  1266.4  618.87  1276.2  618.68  1305.6  627.01  1315.4  628.28  1413.6  631.29
#Mann= 3 , 0 , 0
       0      .1       0   804.9    .045       0   844.2      .1       0
Bank Sta=804.9,844.2
XS Rating Curve= 0 ,0
Exp/Cntr=0.3,0.1

Chan Stop Cuts=-1
Use User Specified Reach Order=0
Composite Channel Slope=5